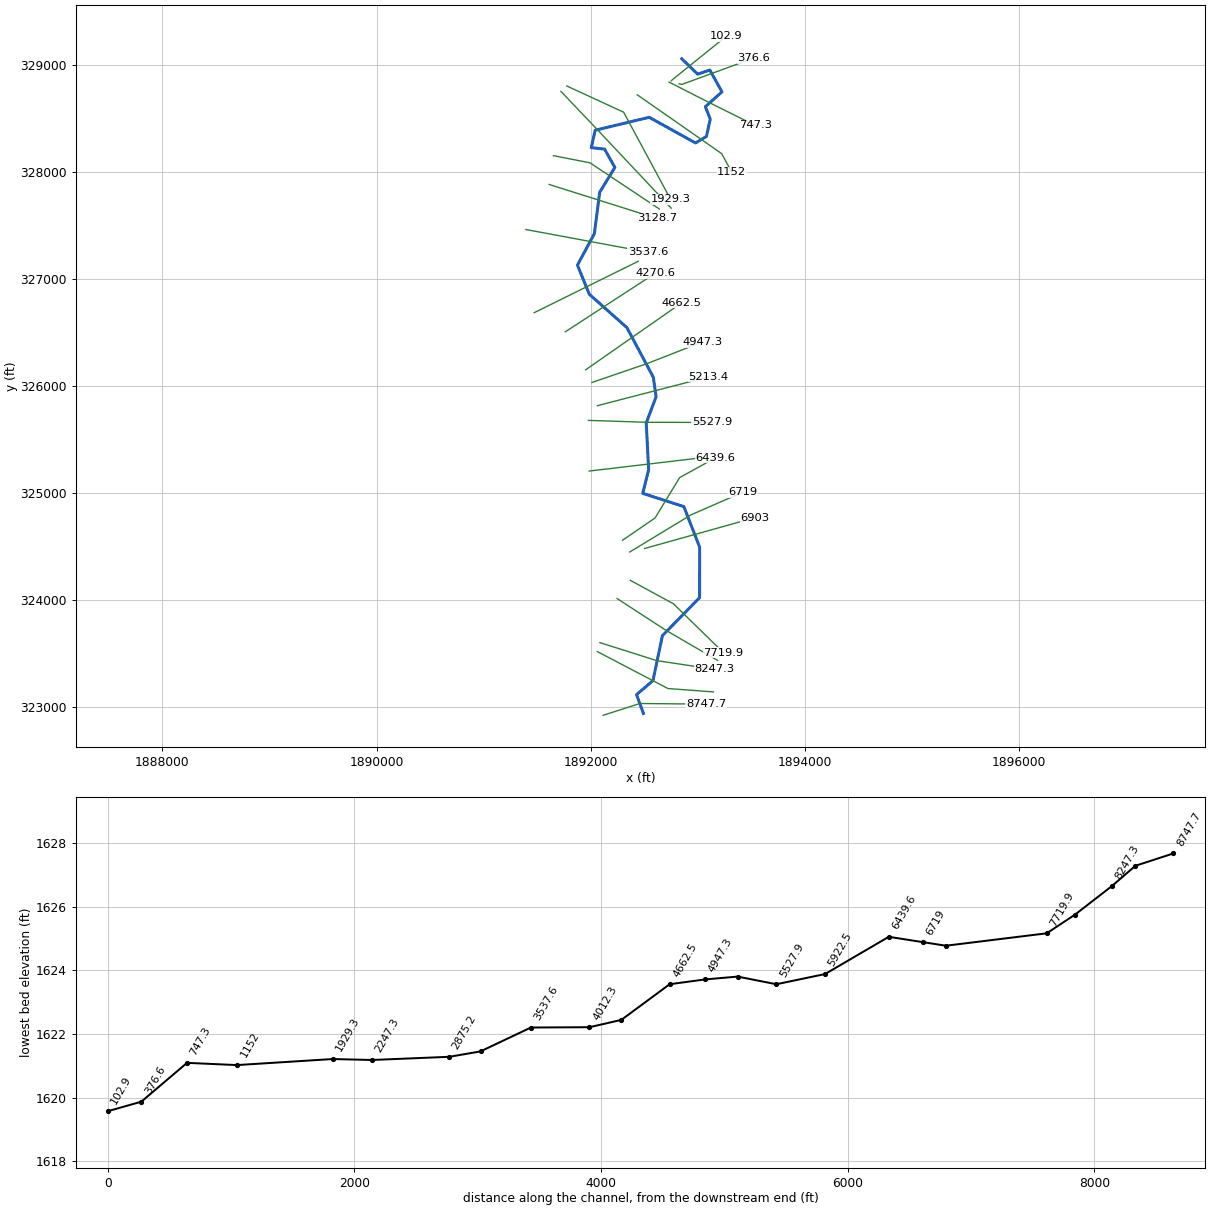
--- PaintCrk.prj (project) ---

Proj Title=PaintCrk
Current Plan=p01
Default Exp/Contr=0,0
English Units
Geom File=g01
Flow File=f01
Plan File=p01
BEGIN DESCRIPTION:
END DESCRIPTION:
DSS Export Rating Curves= 0
DSS Export Rating Curve Sorted= 0
DSS Export Volume Flow Curves= 0
DXF OffsetX= 0
DXF OffsetY= 0
DXF ScaleX= 0
DXF ScaleY= 0

--- PaintCrk.p01 (plan) ---

Plan Title=Floodplain
Program Version=4.00
Geom File=g01
Flow File=f01
K Sum by GR=0
Std Step Tol=0.01
Critical Tol=0.01
Num of Std Step Trials=20
Max Error Tol=0.3
Flow Tol Ratio=0.001
Split Flow NTrial=30
Split Flow Tol=0.02
Split Flow Ratio=0.02
Log Output Level=0
Friction Slope Method=1
Unsteady Friction Slope Method=2
Unsteady Bridges Friction Slope Method=1
Global Log Level=0
CheckData=False
Run HTab=0
Run UNet=0
Run PostProcess=0
UNET Theta=0
UNET Theta Warmup=0
UNET ZTol=0
UNET ZSATol=0
UNET MxIter=0
UNET MaxInSteps=0
UNET DtIC=0
UNET DtMin=0
UNET MaxCRTS=0
UNET WFStab=0
UNET SFStab=0
UNET WFX=0
UNET SFX=0
UNET DSS MLevel=0
UNET DZMax Abort=0
UNET Convert EG Bridges=0
UNET Use Existing IB Tables=0
UNET Froude Limit=0
UNET Froude Power=0
Write IC File=0
Echo Input=False
Echo Output=False
Write Detailed=0

--- PaintCrk.f01 (steady flow) ---

Flow Title=NFF Regression Equation
Program Version=4.10
Number of Profiles= 1
Profile Names=P100yr
River Rch & RM=PaintCrk,Main            ,8747.7
4903.603
River Rch & RM=PaintCrk,Main            ,102.9
5316.157
Boundary for River Rch & Prof#=PaintCrk,Main            , 1
Up Type= 0
Dn Type= 1
Dn Known WS=1630.8
DSS Import GetInterval= 0
DSS Import GetPeak= 0
DSS Import FillOption= 0

--- PaintCrk.g01 (geometry) ---

Geom Title=USGS 3m DEM
Program Version=4.10

River Reach=PaintCrk        ,Main
Reach XY= 30
     1892491.839      322944.285     1892427.603      323119.632
       1892580.9      323250.719     1892668.923      323669.979
     1893016.072      324025.202     1893016.145      324498.104
     1892869.046      324875.455     1892485.263       324998.92
      1892540.45      325220.327     1892517.881      325656.091
     1892609.895      325900.882     1892583.853      326083.174
     1892337.325      326546.715     1891986.631       326857.48
      1891875.52      327130.049     1892033.506      327423.452
     1892083.351      327810.333     1892224.935      328041.911
     1892128.992      328213.382     1892004.686      328226.577
     1892041.162      328389.441     1892545.659      328510.257
     1892977.951      328270.674     1893080.147      328331.878
     1893115.686       328494.02     1893069.964      328609.216
     1893225.177      328747.682     1893111.631      328951.229
     1892998.175      328913.024     1892849.478      329057.132

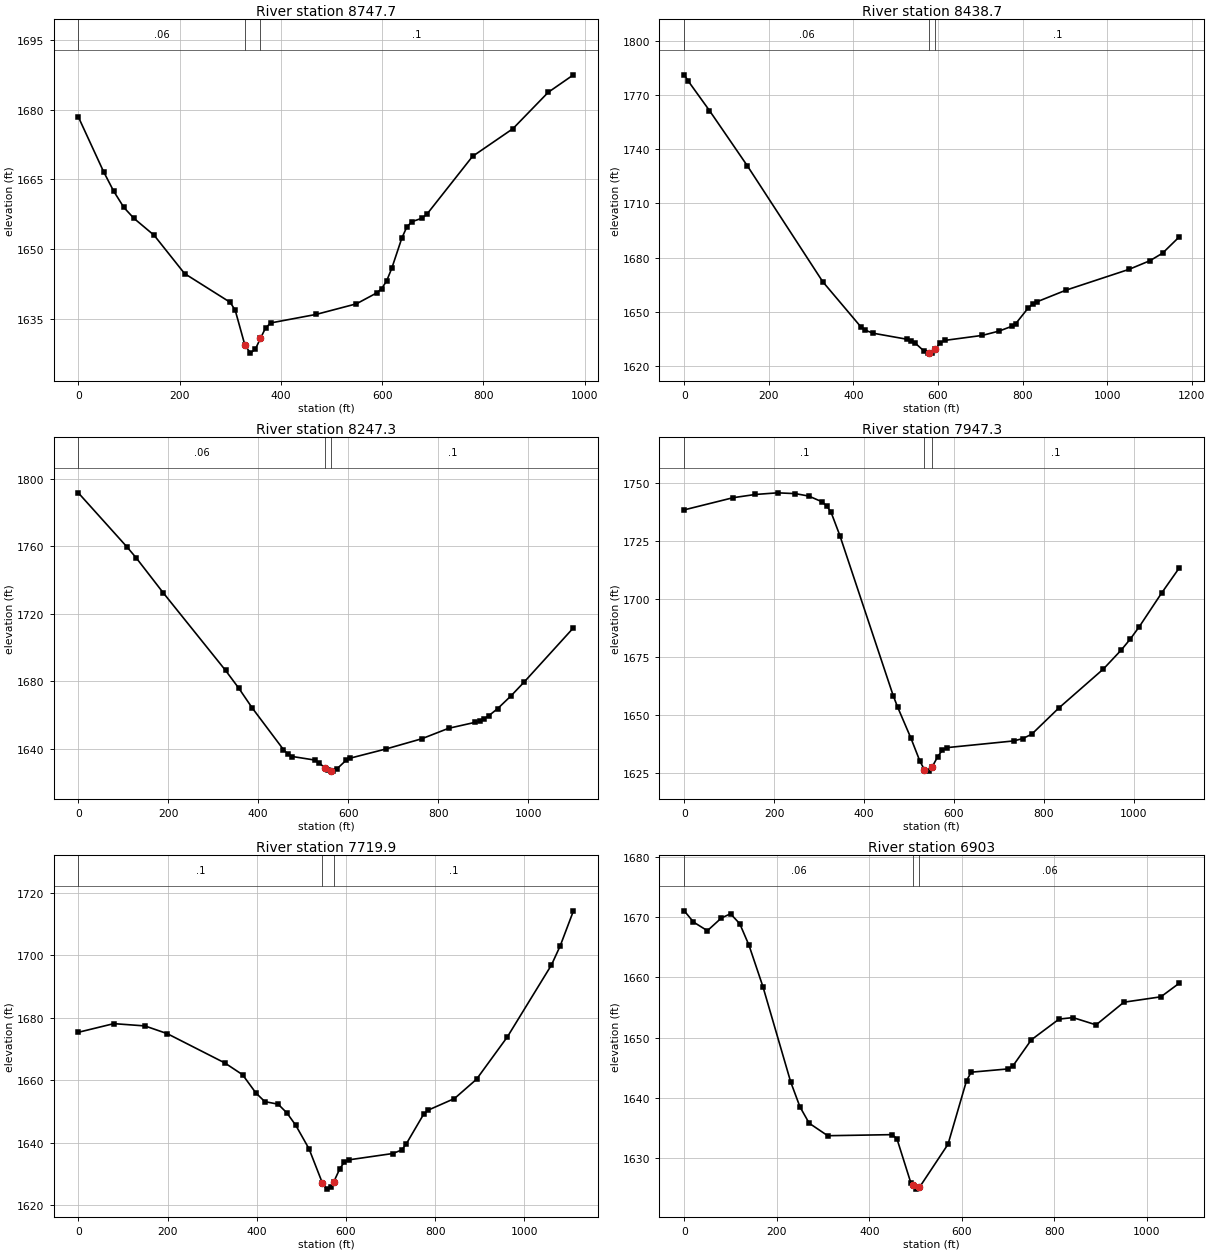
Type RM Length L Ch R = 1 ,8747.7  ,326.9,308.8,290.7
XS GIS Cut Line= 3
     1892116.096      322926.592     1892458.642      323036.837
       1893076.8      323030.931
#Sta/Elev= 30
       0 1678.43      50 1666.63      70 1662.44      90 1658.96     110 1656.61
   149.9 1652.97   209.9 1644.76   299.9 1638.59   309.9 1636.89   328.9 1629.44
   339.9 1627.67   349.8 1628.54   359.8 1630.86   369.8 1633.05   379.8 1634.15
   469.5 1635.98   549.3 1638.26   589.2 1640.59   599.2 1641.52   609.1 1643.21
   619.1 1645.88     639 1652.38     649  1654.8     659  1655.9   678.9 1656.66
   688.9 1657.56   778.6 1669.93   858.4 1675.88   928.2  1683.7     978 1687.45
#Mann= 3 , 0 , 0
       0     .06       0   328.9    .045       0   359.8      .1       0
Bank Sta=328.9,359.8
XS Rating Curve= 0 ,0
Exp/Cntr=0.3,0.1

Type RM Length L Ch R = 1 ,8438.7  ,187.6,191.5,199
XS GIS Cut Line= 3
     1892060.768      323521.859     1892720.473      323176.611
     1893145.703      323145.113
#Sta/Elev= 30
       0 1781.06     9.9 1777.46    59.6 1761.33   148.9  1730.9   327.6 1666.73
     417 1641.99   426.9 1640.06   446.8 1638.28   526.2 1634.97   536.1 1634.18
     546 1632.87   565.9 1628.64   575.8 1627.28   578.9 1627.36   585.7 1627.55
   593.9 1629.57   605.6 1632.91   615.5 1634.29   704.9 1637.08   744.6 1639.47
   774.3 1642.07   784.2 1643.65     814 1652.39   823.9 1654.32   833.8 1655.61
   903.2 1662.11    1052 1673.58  1101.6 1678.38  1131.3 1682.54    1171  1691.6
#Mann= 3 , 0 , 0
       0     .06       0   578.9    .045       0   593.9      .1       0
Bank Sta=578.9,593.9
XS Rating Curve= 0 ,0
Exp/Cntr=0.3,0.1

Type RM Length L Ch R = 1 ,8247.3  ,306,300.1,291.5
XS GIS Cut Line= 3
     1892085.276      323605.188     1892614.763      323437.441
     1893154.216      323356.194
#Sta/Elev= 30
       0  1791.6   109.1 1759.26   128.9 1752.99   188.4 1732.49   327.3 1686.38
   357.1  1675.7   386.8 1664.05   456.2  1639.4   466.2 1636.69   476.1  1635.3
   525.7  1633.2   535.6 1631.58   547.9 1628.58   555.4 1627.05   562.9 1626.74
   565.3 1626.64   575.3 1628.03   595.1 1632.99     605 1634.36   684.4 1639.79
   763.7 1645.82   823.2 1652.01   882.8 1655.59   892.7 1656.45   902.6 1657.75
   912.5 1659.44   932.3 1663.66   962.1 1671.24   991.8 1679.57    1101  1711.6
#Mann= 3 , 0 , 0
       0     .06       0   547.9    .045       0   562.9      .1       0
Bank Sta=547.9,562.9
XS Rating Curve= 0 ,0
Exp/Cntr=0.3,0.1

Type RM Length L Ch R = 1 ,7947.3  ,231.7,227.2,221.6
XS GIS Cut Line= 3
      1892245.62      324016.856     1892701.698      323720.404
     1893183.526      323439.835
#Sta/Elev= 30
       0  1738.6   108.8 1743.86   158.2 1745.25   207.7 1745.96   247.2 1745.61
   276.9 1744.57   306.6 1742.08   316.5 1740.36   326.4 1737.68   346.2  1727.5
   464.8 1658.38   474.7  1653.4   504.4 1639.92   524.2 1630.06   534.1 1626.41
     544 1625.74   551.5 1627.58   563.9 1631.98   573.8 1634.72   583.8 1635.88
   733.1 1638.79     753  1639.8     773 1641.69   832.7  1652.9   932.3 1669.83
   972.1 1678.05     992 1682.74  1011.9 1688.03  1061.7  1702.6  1101.5 1713.61
#Mann= 3 , 0 , 0
       0      .1       0   534.1    .045       0   551.5      .1       0
Bank Sta=534.1,551.5
XS Rating Curve= 0 ,0
Exp/Cntr=0.3,0.1

Type RM Length L Ch R = 1 ,7719.9  ,793.1,816.8,840.5
XS GIS Cut Line= 3
     1892369.342      324186.844     1892771.659      323968.011
     1893238.087      323512.098
#Sta/Elev= 30
       0 1675.33    79.6  1678.1   149.3 1677.37   199.1 1674.92   328.6 1665.52
   368.4 1661.75   398.2 1655.92   418.2 1653.15     448 1652.34   467.9 1649.51
   487.6 1645.57   517.3 1638.06   546.9 1627.24   556.8 1625.16   566.7 1625.92
   572.9 1627.54   586.4 1631.69   596.3 1633.78   606.2 1634.52     705 1636.55
   724.8 1637.66   734.7 1639.47   774.2  1649.1   784.1 1650.41   843.4 1654.14
   892.8  1660.3     962 1673.86  1060.8 1696.85  1080.6 1703.02  1110.2 1714.19
#Mann= 3 , 0 , 0
       0      .1       0   546.9    .045       0   572.9      .1       0
Bank Sta=546.9,572.9
XS Rating Curve= 0 ,0
Exp/Cntr=0.3,0.1

Type RM Length L Ch R = 1 ,6903    ,177.8,183.9,188.5
XS GIS Cut Line= 2
     1892503.183      324484.291     1893533.774      324772.206
#Sta/Elev= 30
       0 1671.09      20 1669.22      50 1667.78      80 1669.88     100  1670.6
     120 1668.94     140 1665.34     170 1658.48     230 1642.62     250 1638.47
     270 1635.74     310 1633.66     450 1633.84     460 1633.06     490 1625.73
   493.3 1625.41     500 1624.77   508.3 1625.07     570 1632.24     610 1642.82
     620 1644.23     700 1644.78     710 1645.25     750 1649.62     810 1653.07
     840 1653.32     890 1652.11     950 1655.88    1030 1656.78    1070 1659.06
#Mann= 3 , 0 , 0
       0     .06       0   493.3    .045       0   508.3     .06       0
Bank Sta=493.3,508.3
XS Rating Curve= 0 ,0
Exp/Cntr=0.3,0.1

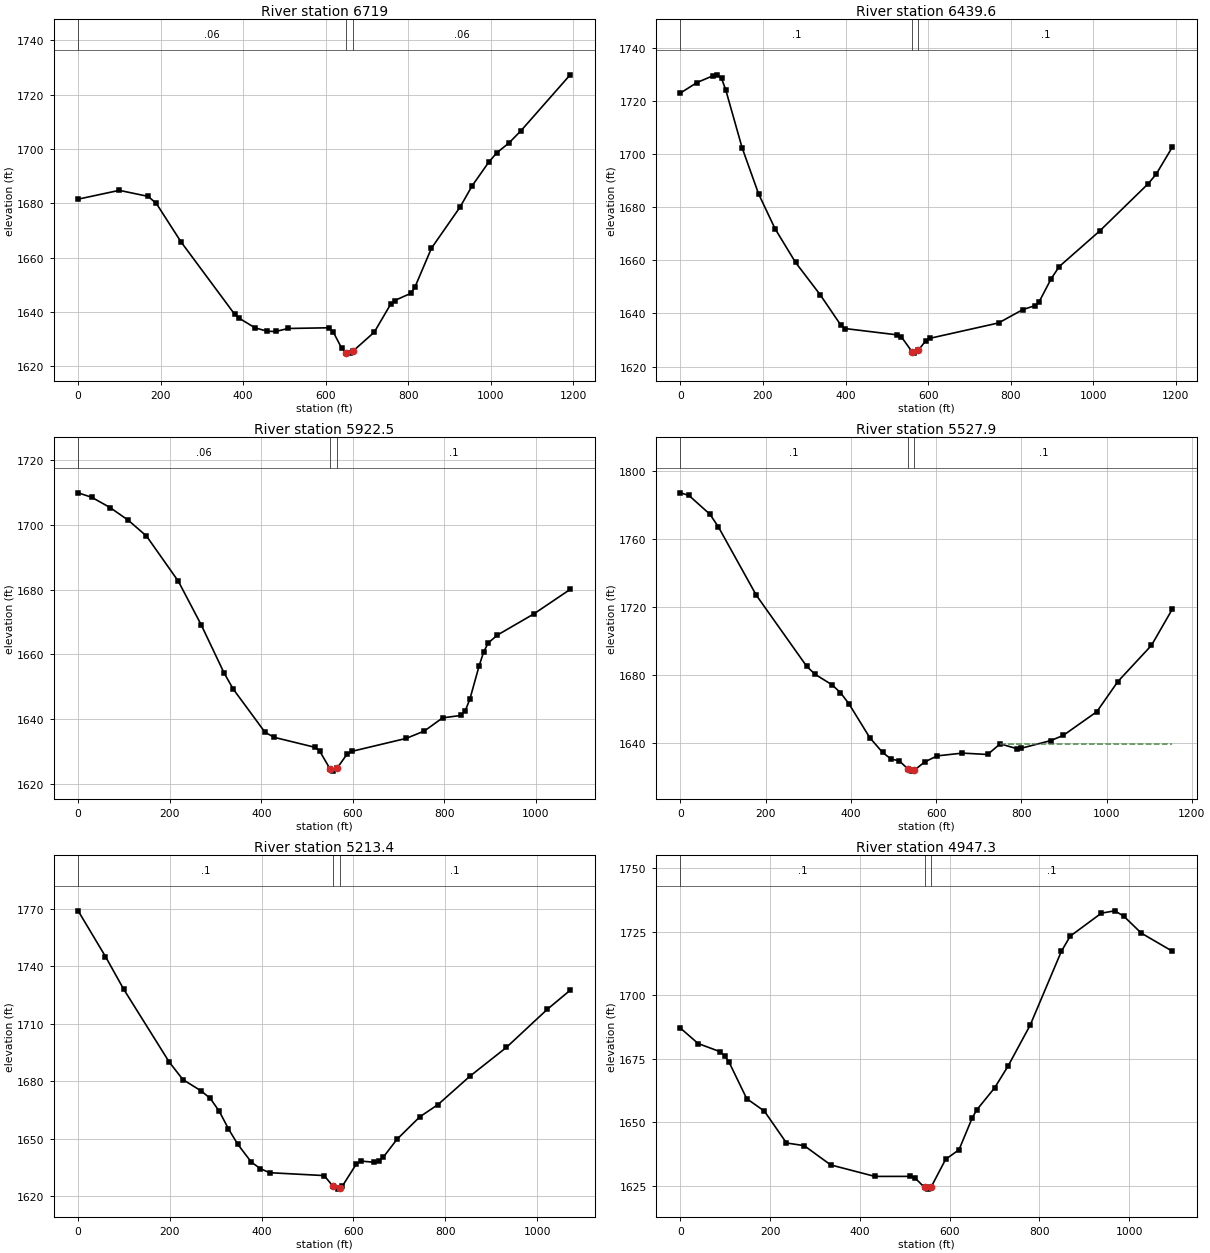
Type RM Length L Ch R = 1 ,6719    ,268.9,279.6,291.8
XS GIS Cut Line= 3
      1892364.67       324451.78     1892936.397      324798.393
     1893416.799       325008.57
#Sta/Elev= 30
       0 1681.54    99.8 1684.78   169.6 1682.56   189.6 1679.96   249.5  1665.8
   379.2 1639.24   389.2 1637.83   429.1 1634.17     459 1632.93     479 1632.84
   508.9 1633.95   608.7 1634.21   618.7 1632.62   638.6 1626.78   650.5 1625.01
   658.6 1624.88   665.5  1625.5   718.1 1632.61   757.6 1642.85   767.5 1644.24
   807.1 1646.91     817 1649.31   856.6 1663.48   925.8 1678.57   955.5 1686.49
   995.1 1695.05  1014.9 1698.58  1044.6 1702.21  1074.2  1706.8    1193 1727.29
#Mann= 3 , 0 , 0
       0     .06       0   650.5    .045       0   665.5     .06       0
Bank Sta=650.5,665.5
XS Rating Curve= 0 ,0
Exp/Cntr=0.3,0.1

Type RM Length L Ch R = 1 ,6439.6  ,537.4,516.7,496.1
XS GIS Cut Line= 4
     1892296.474      324561.068     1892600.632      324769.253
     1892829.903      325146.404     1893164.651       325330.32
#Sta/Elev= 30
       0 1722.99    39.8 1726.91    79.7 1729.54    89.7 1729.84    99.6 1728.48
   109.6 1724.26   149.4 1702.38   189.3 1685.02   229.1 1671.92   278.9 1659.19
   338.7    1647   388.2 1635.67     398 1634.32   525.5 1631.92   535.3 1631.16
   561.3 1625.51   564.8 1625.05   576.3 1626.12   594.2 1629.72     604 1630.62
   770.7 1636.42   829.5 1641.45   858.9 1642.92   868.7 1644.31   898.1 1653.07
   917.7 1657.66  1015.6 1671.04  1133.1 1688.83  1152.7  1692.5  1191.9  1702.7
#Mann= 3 , 0 , 0
       0      .1       0   561.3    .045       0   576.3      .1       0
Bank Sta=561.3,576.3
XS Rating Curve= 0 ,0
Exp/Cntr=0.3,0.1

Type RM Length L Ch R = 1 ,5922.5  ,397.9,394.6,391.8
XS GIS Cut Line= 2
     1891985.146      325207.157     1893052.438      325333.273
#Sta/Elev= 30
       0 1709.95    29.8 1708.56    69.7  1705.4   109.5 1701.47   149.3 1696.58
   218.9 1682.59   268.7 1669.15   318.4 1654.34   338.3 1649.34     408 1635.93
   427.9 1634.34   517.5 1631.24   527.4 1630.12   550.3 1624.54   557.3 1623.88
   565.3 1624.74   587.1 1629.07   597.1 1629.97   716.5    1634   756.3  1636.3
   796.1 1640.36   835.9 1641.09   845.8 1642.63   855.8 1646.23   875.7 1656.38
   885.6 1660.69   895.6  1663.5   915.5 1665.94   995.1 1672.48  1074.7 1680.08
#Mann= 3 , 0 , 0
       0     .06       0   550.3    .045       0   565.3      .1       0
Bank Sta=550.3,565.3
XS Rating Curve= 0 ,0
Exp/Cntr=0.3,0.1

Type RM Length L Ch R = 1 ,5527.9  ,308,314.5,320.4
XS GIS Cut Line= 3
      1891977.66      325680.396     1892520.834      325662.614
     1893132.169      325661.054
#Sta/Elev= 30
       0 1786.95    19.8 1785.44    69.2 1774.37    88.9 1767.02   177.9  1726.9
   296.4 1685.07   316.2 1680.38   355.7 1674.25   375.5 1669.66   395.2 1663.19
   444.6 1643.12   474.3 1634.57   494.1 1630.71   513.8 1629.55   534.1 1624.77
   543.5 1623.56   549.1 1624.09     573 1628.92   602.6 1632.51   661.8 1634.14
     721 1633.33   750.5 1639.59     790 1636.71   799.8 1636.99   868.8 1641.46
   898.4 1644.52   977.3 1658.45  1026.6 1676.14  1105.5  1697.4  1154.8  1718.8
#Mann= 3 , 0 , 0
       0      .1       0   534.1    .045       0   549.1      .1       0
#XS Ineff= 2 , 0
                          750.37         1639.62
Permanent Ineff=
       F       F
Bank Sta=534.1,549.1
XS Rating Curve= 0 ,0
Exp/Cntr=0.3,0.1

Type RM Length L Ch R = 1 ,5213.4  ,264.5,266.1,268.8
XS GIS Cut Line= 2
     1892061.712      325817.562     1893099.686      326086.284
#Sta/Elev= 30
       0 1768.98    59.6 1745.11    99.3 1728.06   198.6 1690.05   228.3 1680.95
     268 1675.04   287.9 1671.14   307.8  1664.3   327.6 1655.23   347.5 1647.31
   377.2 1637.94   397.1 1634.49     417 1632.37   536.1 1630.87   555.3 1625.33
   565.9  1623.8   570.3 1624.51   575.8 1625.39   605.6 1636.67   615.5 1638.46
   645.3 1637.79   655.2 1638.33   665.2 1640.54   694.9 1649.81   744.6 1661.53
   784.3 1667.93   853.8 1682.72   933.2 1697.72  1022.6 1717.65  1072.2 1727.54
#Mann= 3 , 0 , 0
       0      .1       0   555.3    .045       0   570.3      .1       0
Bank Sta=555.3,570.3
XS Rating Curve= 0 ,0
Exp/Cntr=0.3,0.1

Type RM Length L Ch R = 1 ,4947.3  ,278.5,284.8,290.1
XS GIS Cut Line= 3
     1892011.311      326034.455     1892532.952      326213.056
      1893040.26      326412.356
#Sta/Elev= 30
       0 1687.01    39.4 1680.96    88.6 1677.73    98.5 1676.14   108.3 1673.64
   147.7 1659.28   187.1 1654.37   236.3 1641.85   275.7 1640.81   334.8 1633.23
   433.2 1628.71     512 1628.72   521.8 1628.27   543.9 1624.38   551.4 1623.71
   558.9 1624.63     591 1635.44   620.7 1639.18   650.5 1651.83   660.4  1654.9
     700  1663.5   729.8 1672.01   779.3 1688.17   848.7 1717.15   868.5 1723.16
   937.9  1732.2   967.6 1733.13   987.4 1731.11    1027 1724.36  1096.4 1717.22
#Mann= 3 , 0 , 0
       0      .1       0   543.9    .045       0   558.9      .1       0
Bank Sta=543.9,558.9
XS Rating Curve= 0 ,0
Exp/Cntr=0.3,0.1

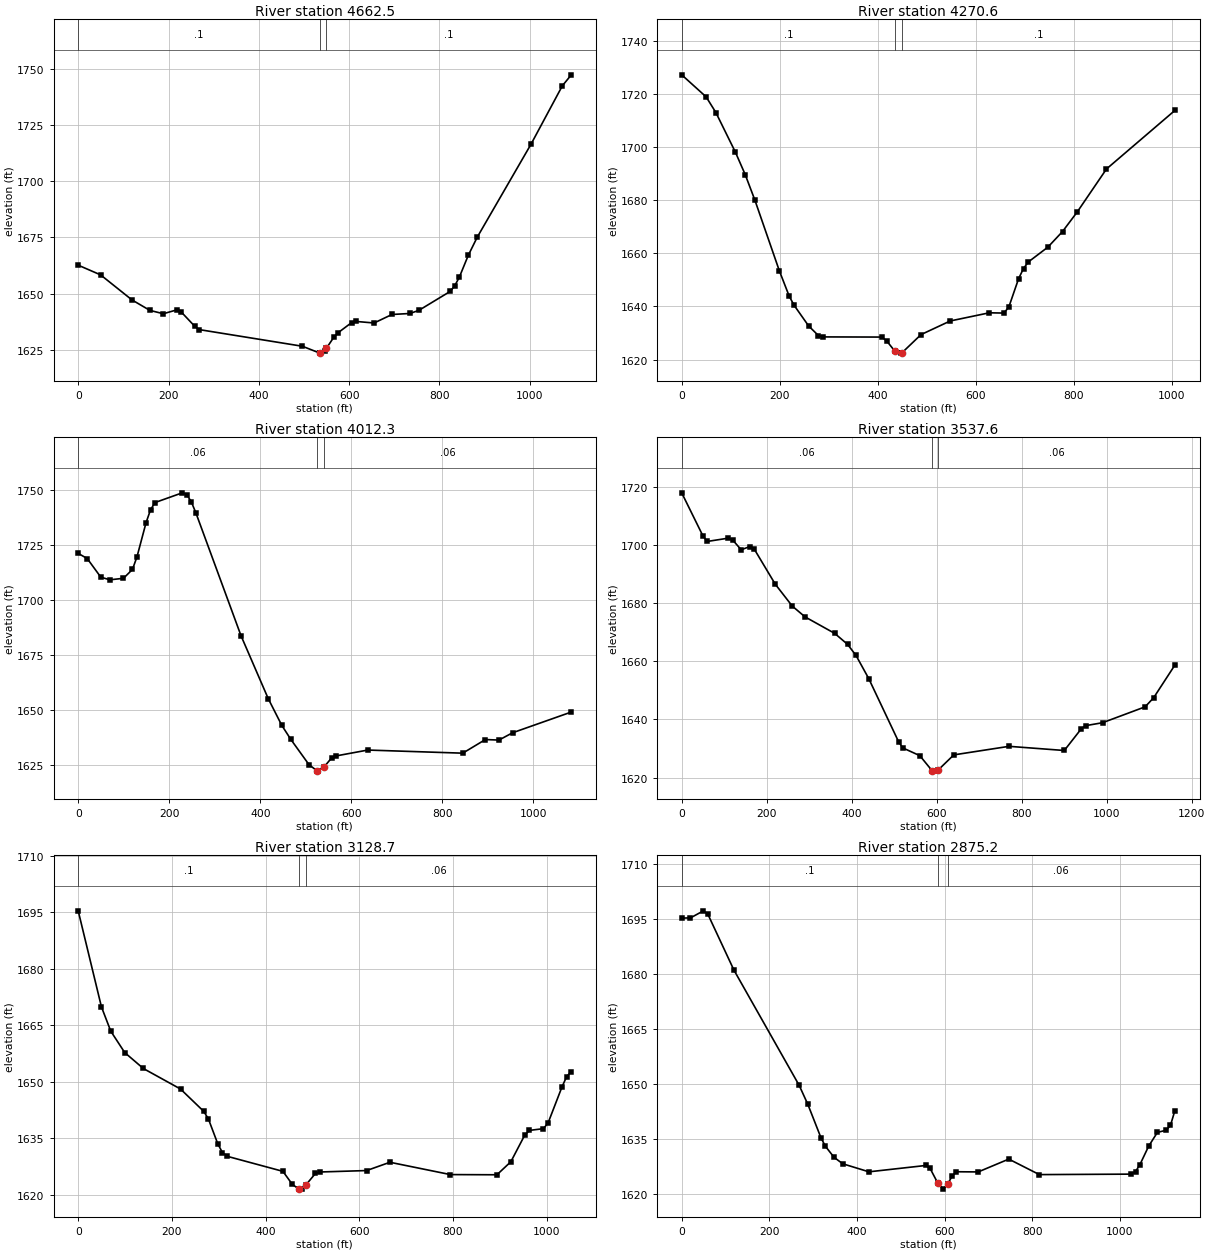
Type RM Length L Ch R = 1 ,4662.5  ,392.6,391.8,391.1
XS GIS Cut Line= 3
     1891952.244      326152.348     1892400.034      326464.759
     1892847.823       326777.17
#Sta/Elev= 30
       0 1662.67    49.6 1658.36   119.1 1647.22   158.8 1642.56   188.6 1641.08
   218.4  1642.8   228.3 1641.83   258.1 1635.49     268 1634.02   496.4 1626.62
   534.7  1623.6   536.1 1623.56     546 1624.62   549.7 1625.74   565.8 1630.56
   575.8 1632.67   605.6 1637.16   615.5 1637.65   655.2 1636.96   694.9 1640.75
   734.6 1641.19   754.5 1642.59     824 1651.04   833.9 1653.57   843.8 1657.24
   863.7 1667.01   883.5 1675.07  1002.6 1716.43  1072.2 1742.48    1092 1747.32
#Mann= 3 , 0 , 0
       0      .1       0   534.7    .045       0   549.7      .1       0
Bank Sta=534.7,549.7
XS Rating Curve= 0 ,0
Exp/Cntr=0.3,0.1

Type RM Length L Ch R = 1 ,4270.6  ,260.9,258.2,255.5
XS GIS Cut Line= 2
     1891761.984      326507.084     1892605.267      327055.962
#Sta/Elev= 30
       0 1727.13    49.8 1718.85    69.7 1712.95   109.6 1698.02   129.5 1689.63
   149.4 1679.95   199.2 1653.43   219.2 1643.93   229.1  1640.5     259 1632.66
   278.9 1629.06   288.9 1628.54   408.4 1628.48   418.4 1626.99   434.8 1623.21
   448.3 1622.44   449.8 1622.63   488.2  1629.4   547.9 1634.54   627.6 1637.61
   657.5 1637.51   667.5 1639.81   687.4 1650.45   697.4 1654.27   707.3 1656.74
   747.2 1662.32     777 1668.18   806.9 1675.51   866.7 1691.71  1006.2 1713.72
#Mann= 3 , 0 , 0
       0      .1       0   434.8    .045       0   449.8      .1       0
Bank Sta=434.8,449.8
XS Rating Curve= 0 ,0
Exp/Cntr=0.3,0.1

Type RM Length L Ch R = 1 ,4012.3  ,488.8,475.4,462
XS GIS Cut Line= 2
      1891471.62      326685.738     1892442.647      327165.599
#Sta/Elev= 30
       0  1721.3    19.9 1718.92    49.7 1710.45    69.6 1709.27    99.4 1709.94
   119.2 1713.99   129.2 1719.78     149 1735.24     159 1741.19   168.9 1744.43
   228.6 1748.84   238.5 1748.01   248.4 1744.75   258.4 1739.76   357.7 1683.77
   417.4 1655.18   447.2 1643.02     467 1636.64   506.8 1625.19     524 1622.43
   526.7 1622.21     539 1623.87   556.5  1628.2   566.4 1629.13     636  1631.8
   844.6 1630.38   894.3 1636.58   924.1 1636.34     954 1639.66  1083.1  1649.1
#Mann= 3 , 0 , 0
       0     .06       0     524    .045       0     539     .06       0
Bank Sta=524,539
XS Rating Curve= 0 ,0
Exp/Cntr=0.3,0.1

Type RM Length L Ch R = 1 ,3537.6  ,411.9,408.1,404.3
XS GIS Cut Line= 2
     1891394.338      327462.374     1892535.094      327250.215
#Sta/Elev= 30
       0 1717.83      50 1703.01      60 1701.12     110 1702.26     120 1701.61
     140 1698.26     160 1699.36     170 1698.66   220.1 1686.44   260.1 1678.92
   290.1 1675.21   360.1 1669.52   390.1 1665.78   410.1 1661.96   440.1 1653.99
   510.1 1632.37   520.1 1630.18   560.2 1627.52   589.1 1622.36   600.2  1622.2
   604.1 1622.68   640.2 1627.78   770.2 1630.72   900.2 1629.29   940.3 1636.77
   950.3 1637.82   990.3 1638.84  1090.3 1644.29  1110.3 1647.39  1160.3 1658.62
#Mann= 3 , 0 , 0
       0     .06       0   589.1    .045       0   604.1     .06       0
Bank Sta=589.1,604.1
XS Rating Curve= 0 ,0
Exp/Cntr=0.3,0.1

Type RM Length L Ch R = 1 ,3128.7  ,259.7,253.4,247.1
XS GIS Cut Line= 2
     1891611.382      327883.174     1892615.157      327566.526
#Sta/Elev= 30
       0 1695.32    49.6 1669.83    69.5 1663.38    99.3  1657.7     139 1653.47
   218.4 1648.02   268.1 1642.07     278 1640.04   297.9 1633.48   307.8 1631.16
   317.8 1630.17   436.9 1626.17   456.8 1622.75   470.7 1621.48   476.6 1621.45
   485.7 1622.52   506.4 1625.62   516.3    1626   615.6 1626.38   665.3 1628.58
   794.4 1625.31   893.7 1625.26   923.4 1628.72   953.2 1635.82   963.2 1637.04
     993  1637.5  1002.9 1639.03  1032.7 1648.63  1042.6 1651.33  1052.5 1652.66
#Mann= 3 , 0 , 0
       0      .1       0   470.7    .045       0   485.7     .06       0
Bank Sta=470.7,485.7
XS Rating Curve= 0 ,0
Exp/Cntr=0.3,0.1

Type RM Length L Ch R = 1 ,2875.2  ,633.2,627.5,622.1
XS GIS Cut Line= 3
     1891651.248      328151.896     1891992.317      328085.453
     1892639.749       327654.52
#Sta/Elev= 30
       0 1695.19    19.9 1695.24    49.6 1697.17    59.6 1696.27   119.1 1681.02
   268.1 1649.56   287.9 1644.37   317.7  1635.3   327.6 1633.01   347.5 1629.97
   367.4 1628.19   427.2    1626   556.9 1627.73   566.8 1626.91   583.8 1623.04
   596.8 1621.28   606.7 1622.59   616.7 1624.79   626.7 1626.02   676.5 1625.97
   746.3 1629.47   816.1 1625.24  1025.5 1625.37  1035.5 1626.07  1045.4 1627.94
  1065.4 1632.98  1085.3 1636.74  1105.3 1637.35  1115.2 1638.66  1125.2 1642.66
#Mann= 3 , 0 , 0
       0      .1       0   583.8    .045       0   606.7     .06       0
Bank Sta=583.8,606.7
XS Rating Curve= 0 ,0
Exp/Cntr=0.3,0.1

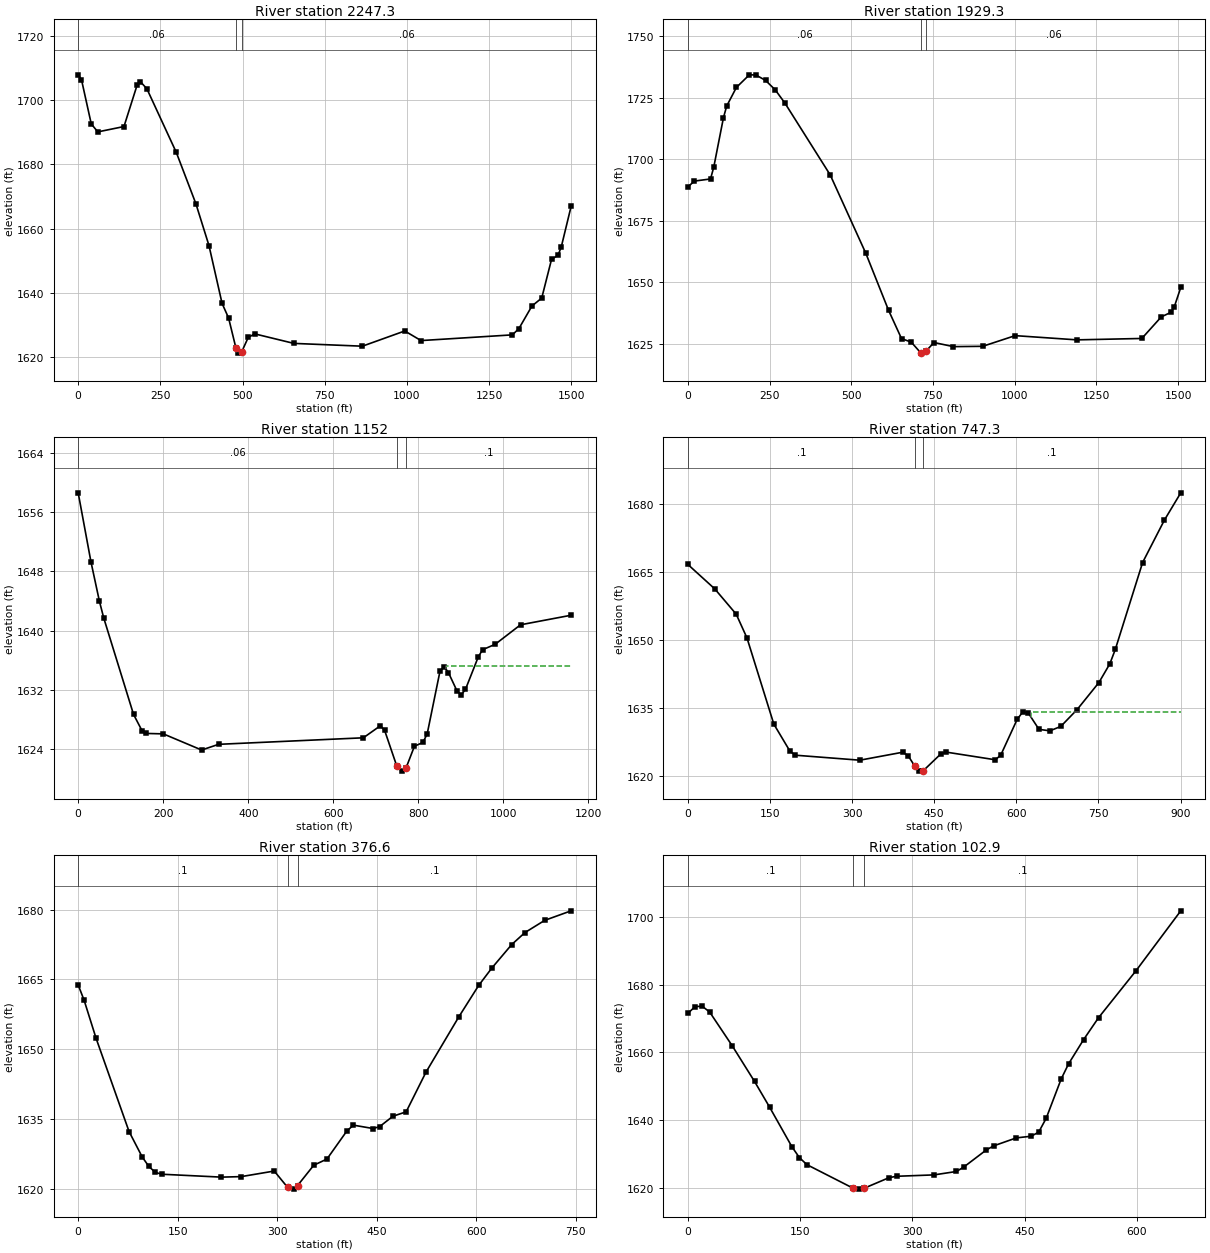
Type RM Length L Ch R = 1 ,2247.3  ,323.7,317.8,311.4
XS GIS Cut Line= 3
      1891721.49      328752.151     1892057.628       328398.95
     1892751.234        327661.7
#Sta/Elev= 30
       0 1707.88      10 1706.39    39.8 1692.59    59.7  1690.1   139.3 1691.77
   179.1 1704.62   189.1 1705.76     209 1703.54   298.5 1683.72   358.2 1667.71
     398 1654.68   437.8 1636.68   457.7 1632.11   480.1 1622.72   487.6 1621.18
   497.5 1621.58   517.4 1626.06   537.2 1627.18   656.3 1624.21   864.7 1623.34
   993.7 1628.08  1043.3 1625.09  1321.2 1626.87    1341 1628.82  1380.7 1635.86
  1410.5 1638.34  1440.3 1650.38  1460.1 1651.67    1470 1654.29  1499.8 1666.86
#Mann= 3 , 0 , 0
       0     .06       0   480.1    .045       0   497.5     .06       0
Bank Sta=480.1,497.5
XS Rating Curve= 0 ,0
Exp/Cntr=0.3,0.1

Type RM Length L Ch R = 1 ,1929.3  ,766.4,776.9,787.7
XS GIS Cut Line= 3
     1891776.318      328802.659      1892306.81      328557.931
     1892745.328      327744.384
#Sta/Elev= 30
       0 1688.76    19.8 1691.13    69.3    1692    79.2 1696.79   108.9 1716.92
   118.8 1721.63   148.5  1729.2   188.1 1734.32   207.9 1734.26   237.6 1732.07
   267.4 1728.21   297.1 1722.81   435.7 1693.61   544.6 1661.77     614 1638.67
   653.8 1627.11   683.6 1625.68   713.4 1621.21   713.9 1621.22   728.9 1622.06
   753.2 1625.52   812.8 1623.85   902.2 1623.98  1001.6 1628.32  1190.4  1626.6
  1389.2 1627.17  1448.8 1635.95  1478.6 1637.81  1488.6 1640.04  1508.4  1647.9
#Mann= 3 , 0 , 0
       0     .06       0   713.9    .045       0   728.9     .06       0
Bank Sta=713.9,728.9
XS Rating Curve= 0 ,0
Exp/Cntr=0.3,0.1

Type RM Length L Ch R = 1 ,1152    ,399.8,404.1,408.7
XS GIS Cut Line= 3
     1892433.788      328720.345     1893222.235       328171.09
      1893316.73      327996.864
#Sta/Elev= 30
       0  1658.6      30 1649.29      50 1643.94    60.1  1641.7   130.1 1628.69
   150.1 1626.48   160.2 1626.11   200.2 1626.05   290.3 1623.87   330.3 1624.64
   670.6 1625.52   710.7 1627.15   720.7 1626.51     749 1621.74   760.7 1621.02
   770.7  1621.4   790.7 1624.38   810.8  1624.9   820.8 1626.07   850.8 1634.51
   860.8 1635.13   870.8 1634.31   890.8 1631.85   900.8 1631.31   910.8 1632.07
   940.9 1636.45   950.9 1637.41   980.7 1638.15  1040.2 1640.78  1159.1 1642.07
#Mann= 3 , 0 , 0
       0     .06       0     749    .045       0   770.7      .1       0
#XS Ineff= 2 , 0
                          864.73         1635.24
Permanent Ineff=
       F       F
Bank Sta=749,770.7
XS Rating Curve= 0 ,0
Exp/Cntr=0.3,0.1

Type RM Length L Ch R = 1 ,747.3   ,353.3,370.6,387.5
XS GIS Cut Line= 3
     1892730.809      328838.956      1893106.88      328647.342
     1893535.144       328434.55
#Sta/Elev= 30
       0 1666.64    49.1 1661.26    88.3 1655.68     108 1650.43     157 1631.45
   186.5 1625.48   196.3  1624.6   314.1  1623.5   392.6 1625.26   402.4 1624.48
   414.6 1622.15   422.1 1621.09   429.6 1621.14   461.9 1624.87   471.9 1625.28
   561.6 1623.59   571.5 1624.62   601.4 1632.48   611.4 1634.08   621.3 1633.99
   641.3  1630.3   661.2 1629.97   681.1 1630.94     711 1634.66   750.8 1640.62
   770.8 1644.76   780.7 1647.91   830.6 1667.07   870.4 1676.42   900.3 1682.43
#Mann= 3 , 0 , 0
       0      .1       0   414.6    .045       0   429.6      .1       0
#XS Ineff= 2 , 0
                          627.48         1634.13
Permanent Ineff=
       F       F
Bank Sta=414.6,429.6
XS Rating Curve= 0 ,0
Exp/Cntr=0.3,0.1

Type RM Length L Ch R = 1 ,376.6   ,264.6,273.1,281.6
XS GIS Cut Line= 3
     1892824.566      328823.207     1892850.897      328817.301
     1893523.324      329063.844
#Sta/Elev= 30
       0 1663.78       9 1660.46      27  1652.3    76.7 1632.26    96.6 1626.77
   106.6 1624.74   116.5 1623.45   126.5 1623.07     216 1622.45   245.8 1622.56
   295.6 1623.76   315.7 1620.26   325.4 1619.87   330.7 1620.63   355.2 1625.01
   375.1 1626.34     405 1632.35   414.9 1633.63   444.8  1632.9   454.7 1633.33
   474.6 1635.55   494.5 1636.49   524.4 1645.02   574.1 1656.96   603.9 1663.68
   623.8 1667.43   653.7 1672.47   673.6 1675.04   703.4 1677.67   743.2 1679.72
#Mann= 3 , 0 , 0
       0      .1       0   315.7    .045       0   330.7      .1       0
Bank Sta=315.7,330.7
XS Rating Curve= 0 ,0
Exp/Cntr=0.3,0.1

Type RM Length L Ch R = 1 ,102.9   ,93.8,102.9,112
XS GIS Cut Line= 3
      1892751.48      328851.753     1892765.854      328864.348
     1893264.109      329265.577
#Sta/Elev= 30
       0 1671.57     9.6 1673.55    19.1 1673.68    29.1 1671.96    59.1 1662.03
    89.1 1651.42   109.1 1643.87   139.1 1632.08   149.1 1628.89     159 1626.82
   220.8 1619.85     229 1619.57   235.8 1619.85     269 1622.97     279 1623.37
     329 1623.78     359 1624.79     369 1626.14     399 1631.18   408.9 1632.38
   438.9 1634.72   458.9 1635.22   468.9 1636.44   478.9 1640.51   498.9 1652.12
   508.9 1656.65   528.9 1663.79   548.9 1670.28   598.9 1684.15   658.8 1701.89
#Mann= 3 , 0 , 0
       0      .1       0   220.8    .045       0   235.8      .1       0
Bank Sta=220.8,235.8
XS Rating Curve= 0 ,0
Exp/Cntr=0.3,0.1

Chan Stop Cuts=-1
Use User Specified Reach Order=0
Composite Channel Slope=5